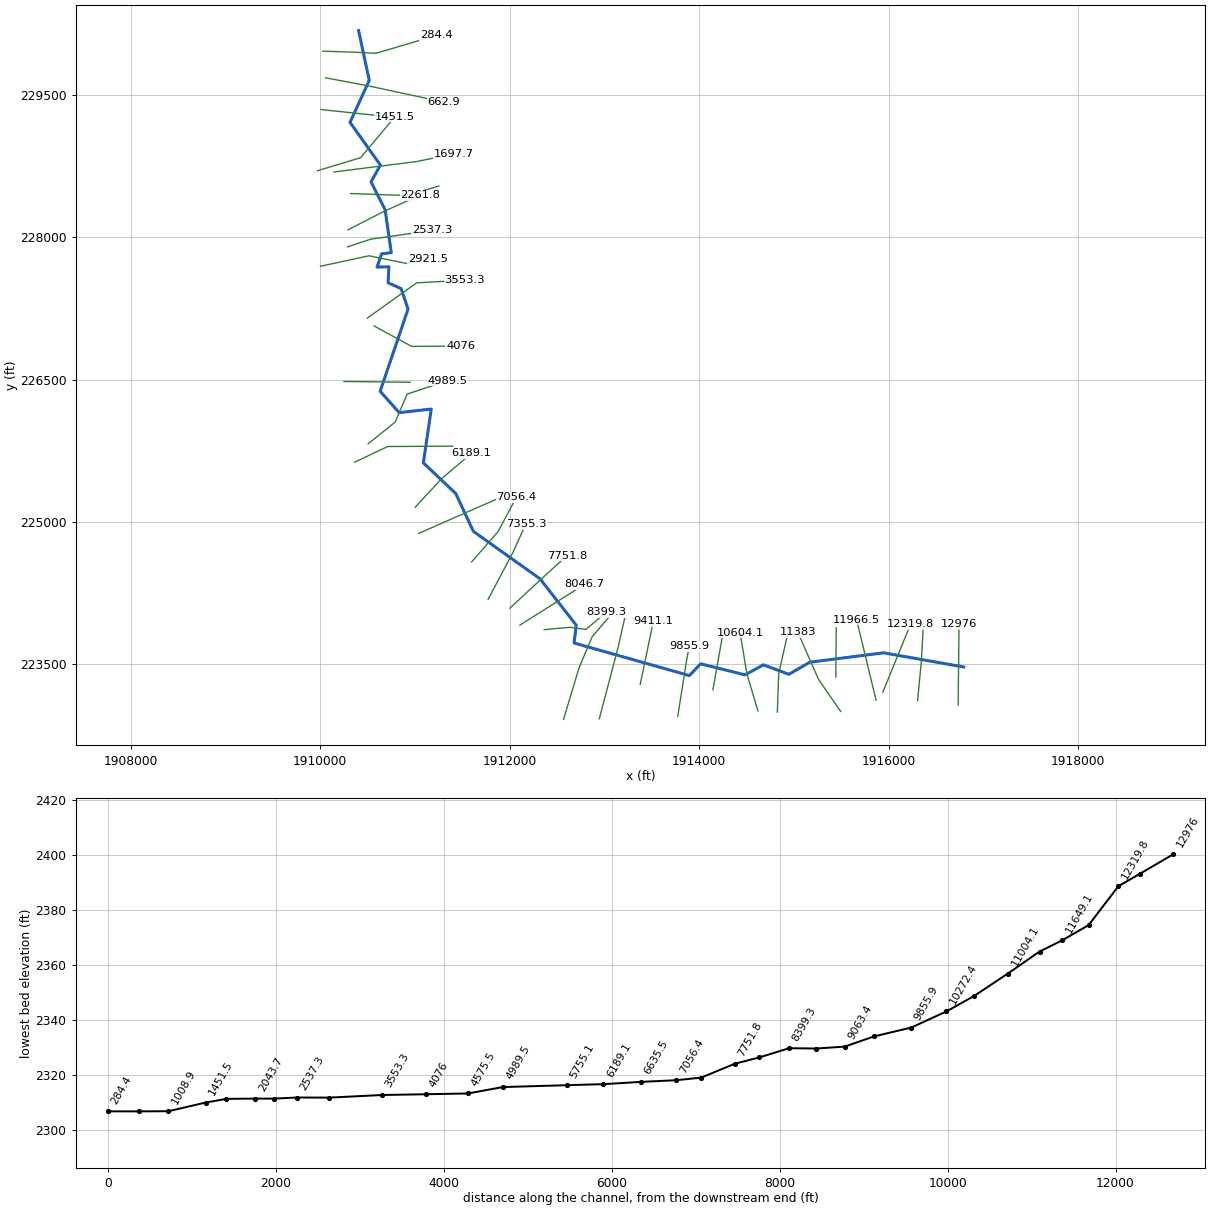
--- PnyCrk2.prj (project) ---

Proj Title=PnyCrk2
Current Plan=p01
Default Exp/Contr=0,0
English Units
Geom File=g01
Flow File=f01
Plan File=p01
BEGIN DESCRIPTION:
END DESCRIPTION:
DSS Export Rating Curves= 0
DSS Export Rating Curve Sorted= 0
DSS Export Volume Flow Curves= 0
DXF OffsetX= 0
DXF OffsetY= 0
DXF ScaleX= 0
DXF ScaleY= 0

--- PnyCrk2.p01 (plan) ---

Plan Title=Floodplain
Program Version=4.00
Geom File=g01
Flow File=f01
K Sum by GR=0
Std Step Tol=0.01
Critical Tol=0.01
Num of Std Step Trials=20
Max Error Tol=0.3
Flow Tol Ratio=0.001
Split Flow NTrial=30
Split Flow Tol=0.02
Split Flow Ratio=0.02
Log Output Level=0
Friction Slope Method=1
Unsteady Friction Slope Method=2
Unsteady Bridges Friction Slope Method=1
Global Log Level=0
CheckData=False
Run HTab=0
Run UNet=0
Run PostProcess=0
UNET Theta=0
UNET Theta Warmup=0
UNET ZTol=0
UNET ZSATol=0
UNET MxIter=0
UNET MaxInSteps=0
UNET DtIC=0
UNET DtMin=0
UNET MaxCRTS=0
UNET WFStab=0
UNET SFStab=0
UNET WFX=0
UNET SFX=0
UNET DSS MLevel=0
UNET DZMax Abort=0
UNET Convert EG Bridges=0
UNET Use Existing IB Tables=0
UNET Froude Limit=0
UNET Froude Power=0
Write IC File=0
Echo Input=False
Echo Output=False
Write Detailed=0

--- PnyCrk2.f01 (steady flow) ---

Flow Title=NFF Regression Equation
Program Version=4.10
Number of Profiles= 1
Profile Names=P100yr
River Rch & RM=PnyCrk2,Main            ,12976
726.6639
River Rch & RM=PnyCrk2,Main            ,8724.4
788.7079
River Rch & RM=PnyCrk2,Main            ,8399.3
 878.662
River Rch & RM=PnyCrk2,Main            ,4989.5
962.8261
River Rch & RM=PnyCrk2,Main            ,3553.3
1050.388
River Rch & RM=PnyCrk2,Main            ,284.4
1161.573
Boundary for River Rch & Prof#=PnyCrk2,Main            , 1
Up Type= 0
Dn Type= 1
Dn Known WS=2320.1
DSS Import GetInterval= 0
DSS Import GetPeak= 0
DSS Import FillOption= 0

--- PnyCrk2.g01 (geometry) ---

Geom Title=USGS 3m DEM
Program Version=4.10

River Reach=PnyCrk2         ,Main
Reach XY= 30
     1916790.552      223468.226     1915945.634      223617.419
       1915167.7      223518.464     1914946.774      223390.763
     1914677.197      223490.562     1914484.415      223385.059
     1914015.493      223500.999     1913896.957      223377.259
     1912680.368      223721.168     1912702.976      223909.714
     1912319.337      224399.919     1911618.087      224898.257
     1911431.793       225298.12     1911089.985      225621.655
     1911173.365      226189.571     1910834.697      226151.806
     1910634.107      226377.155      1910928.51      227244.655
     1910855.573       227459.58     1910717.503      227522.107
     1910726.625      227690.138     1910601.579      227687.536
     1910648.475      227826.909     1910751.378      227839.932
     1910686.261      228293.226     1910537.777      228586.307
     1910636.777      228763.453     1910316.282      229214.301
     1910519.123      229657.926     1910406.568       230182.93

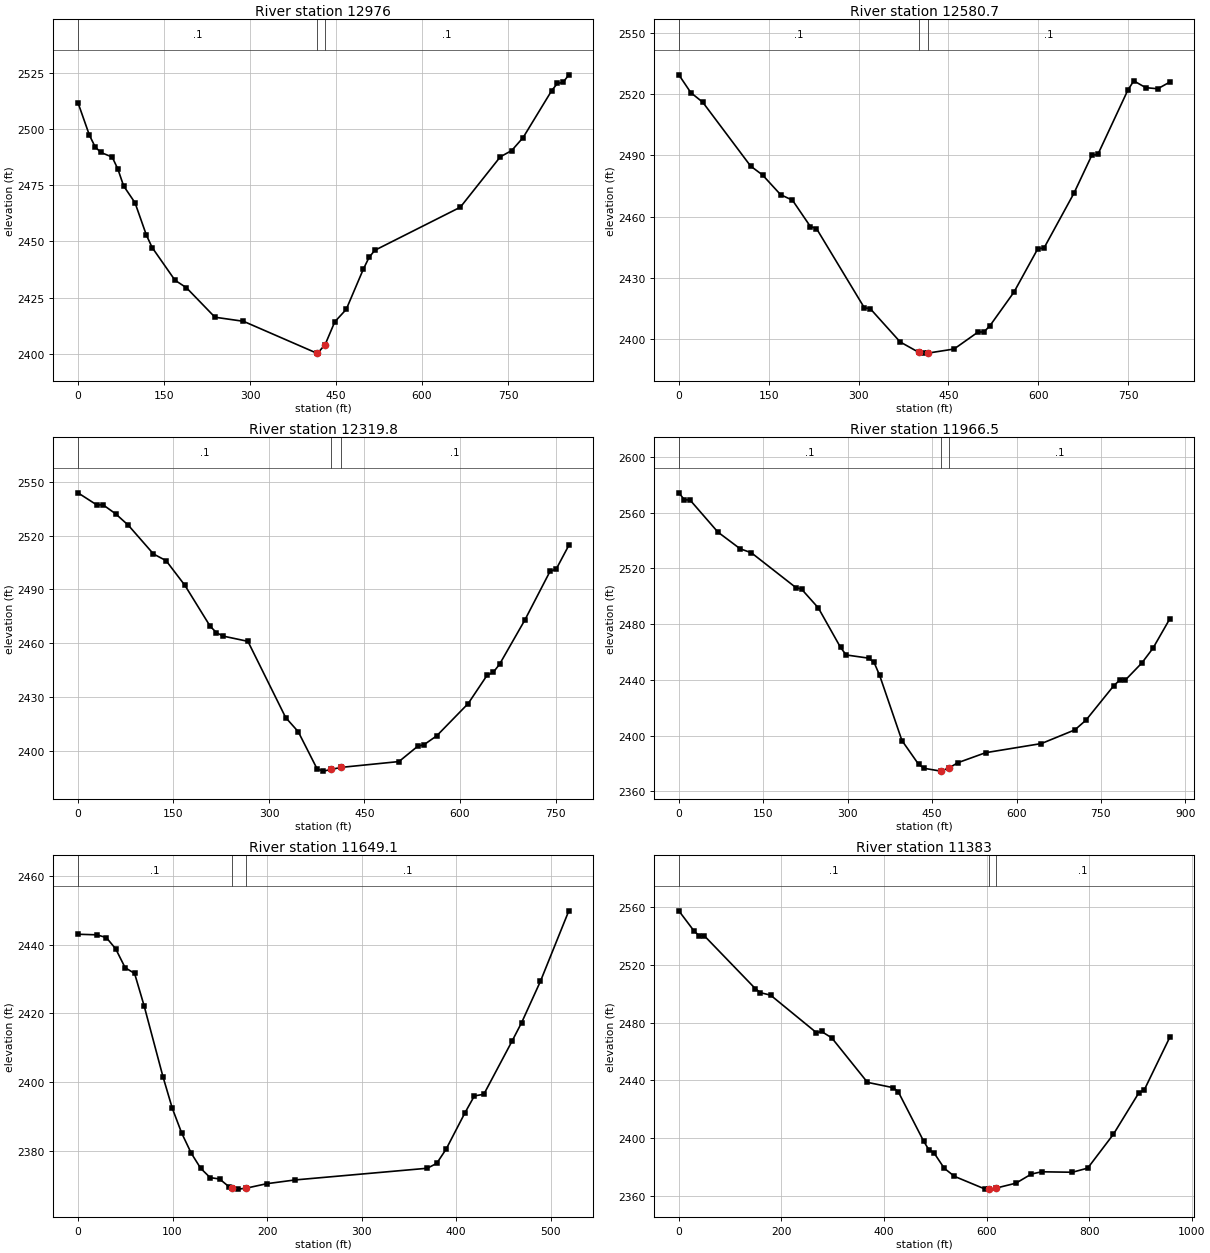
Type RM Length L Ch R = 1 ,12976   ,397.3,395.3,394.3
XS GIS Cut Line= 2
      1916732.78      223065.409     1916741.875      223921.313
#Sta/Elev= 30
       0 2511.62    19.9 2497.19    29.9 2491.98    39.8 2489.49    59.7 2487.43
    69.7 2482.02    79.6 2474.61    99.5 2467.11   119.4 2452.69   129.4 2447.21
   169.2 2432.68   189.1 2429.36   238.9 2416.24   288.6 2414.43   416.1  2400.3
     418 2400.28   431.1 2404.11   447.9 2414.22   467.8 2419.71   497.6 2437.57
   507.6 2442.81   517.6 2445.98   666.8 2465.14   736.5 2487.53   756.4 2490.33
   776.3  2496.1   826.1 2516.95     836 2520.15     846 2520.63     856 2523.98
#Mann= 3 , 0 , 0
       0      .1       0   416.1    .045       0   431.1      .1       0
Bank Sta=416.1,431.1
XS Rating Curve= 0 ,0
Exp/Cntr=0.3,0.1

Type RM Length L Ch R = 1 ,12580.7 ,267.4,260.9,253.5
XS GIS Cut Line= 3
     1916304.229      223112.502     1916343.994      223519.987
     1916366.455       223929.32
#Sta/Elev= 30
       0 2529.38      20 2520.66    39.9 2515.97   119.8 2484.74   139.8 2480.36
   169.8 2470.76   189.7 2468.02   219.7 2455.11   229.7 2454.19   309.6 2415.42
   319.6 2414.94   369.5 2398.68   400.8 2393.56   409.4 2393.22   415.8 2393.23
   459.4 2395.23   499.4 2403.52   509.4 2403.59   519.4 2406.67   559.4 2423.06
   599.4  2444.4   609.4 2444.55   659.4 2471.38   689.4 2490.06   699.4  2490.4
   749.4 2521.83   759.4 2526.43   779.4  2523.1   799.4 2522.56   819.4 2525.81
#Mann= 3 , 0 , 0
       0      .1       0   400.8    .045       0   415.8      .1       0
Bank Sta=400.8,415.8
XS Rating Curve= 0 ,0
Exp/Cntr=0.3,0.1

Type RM Length L Ch R = 1 ,12319.8 ,338.8,353.4,367.9
XS GIS Cut Line= 2
     1915938.684      223203.333     1916229.457      223917.326
#Sta/Elev= 30
       0 2543.94    29.6 2537.18    39.5 2537.23    59.3 2532.18    79.1 2525.85
   118.6  2509.8   138.4 2506.08     168 2492.27   207.6 2469.48   217.4 2465.93
   227.3 2464.02   266.9 2461.04   326.2 2418.51   345.9 2410.62   375.6 2389.83
   385.5  2388.6   397.5 2389.53   412.5 2390.66   504.1 2393.94   533.7 2402.52
   543.6 2403.38   563.4  2408.3   612.8  2426.3   642.4 2442.04   652.3 2443.78
   662.2  2448.3   701.8 2472.92   741.3 2500.06   751.2 2501.44   770.9 2514.63
#Mann= 3 , 0 , 0
       0      .1       0   397.5    .045       0   412.5      .1       0
Bank Sta=397.5,412.5
XS Rating Curve= 0 ,0
Exp/Cntr=0.3,0.1

Type RM Length L Ch R = 1 ,11966.5 ,322.7,317.2,311.6
XS GIS Cut Line= 2
     1915866.206      223119.602     1915661.174      223967.308
#Sta/Elev= 30
       0 2574.33     9.9 2569.33    19.8 2569.21    69.4 2546.13     109 2534.13
   128.8 2531.29   208.1 2506.24     218 2505.18   247.8 2491.71   287.4 2463.26
   297.3 2457.91     337 2455.62   346.9 2452.53   356.8 2443.21   396.4 2396.45
   426.2 2379.26   436.1 2376.49   465.4 2374.48   480.4 2376.81   495.5 2380.49
   545.1 2387.72   644.2 2394.28   703.7 2404.11   723.5 2411.13     773 2435.92
     783 2439.69   792.9 2439.69   822.6 2452.11   842.4 2462.71   872.2 2483.74
#Mann= 3 , 0 , 0
       0      .1       0   465.4    .045       0   480.4      .1       0
Bank Sta=465.4,480.4
XS Rating Curve= 0 ,0
Exp/Cntr=0.3,0.1

Type RM Length L Ch R = 1 ,11649.1 ,256.4,266,275.6
XS GIS Cut Line= 2
      1915442.17      223361.478      1915446.34       223880.64
#Sta/Elev= 30
       0 2443.04      20 2442.87      30 2442.07    39.9  2438.8    49.9 2433.31
    59.9 2431.64    69.9  2422.3    89.9 2401.62    99.8  2392.4   109.8 2385.16
   119.8 2379.37   129.8 2374.97   139.8 2372.26   149.8 2371.86   159.8 2369.59
   162.8 2369.38   169.7 2368.91   177.8 2369.18   199.7 2370.49   229.6 2371.58
   369.4 2374.98   379.4 2376.38   389.4 2380.53   409.4 2391.14   419.3 2396.02
   429.3  2396.5   459.3 2412.04   469.3 2417.35   489.2 2429.38   519.2 2449.85
#Mann= 3 , 0 , 0
       0      .1       0   162.8    .045       0   177.8      .1       0
Bank Sta=162.8,177.8
XS Rating Curve= 0 ,0
Exp/Cntr=0.3,0.1

Type RM Length L Ch R = 1 ,11383   ,389.3,378.9,364.2
XS GIS Cut Line= 3
     1915493.612      222998.902     1915261.355      223333.809
     1915039.767      223836.856
#Sta/Elev= 30
       0 2557.25    29.8 2543.22    39.8 2540.02    49.7 2539.98   149.1 2503.48
     159 2500.67   178.9 2498.96   268.4    2473   278.3 2473.84   298.2 2469.43
   367.8 2438.68   417.6 2435.03   427.6 2432.35   477.5 2397.94   487.5 2392.12
   497.5 2389.97   517.5 2379.31   537.5  2373.7   597.4 2364.88   604.3  2364.9
   619.3 2365.66   657.4    2369   687.4  2375.3   707.4 2376.86   767.4 2376.55
   797.3  2379.4   847.3 2402.75   897.3 2431.63   907.3 2433.25   957.2 2469.75
#Mann= 3 , 0 , 0
       0      .1       0   604.3    .045       0   619.3      .1       0
Bank Sta=604.3,619.3
XS Rating Curve= 0 ,0
Exp/Cntr=0.3,0.1

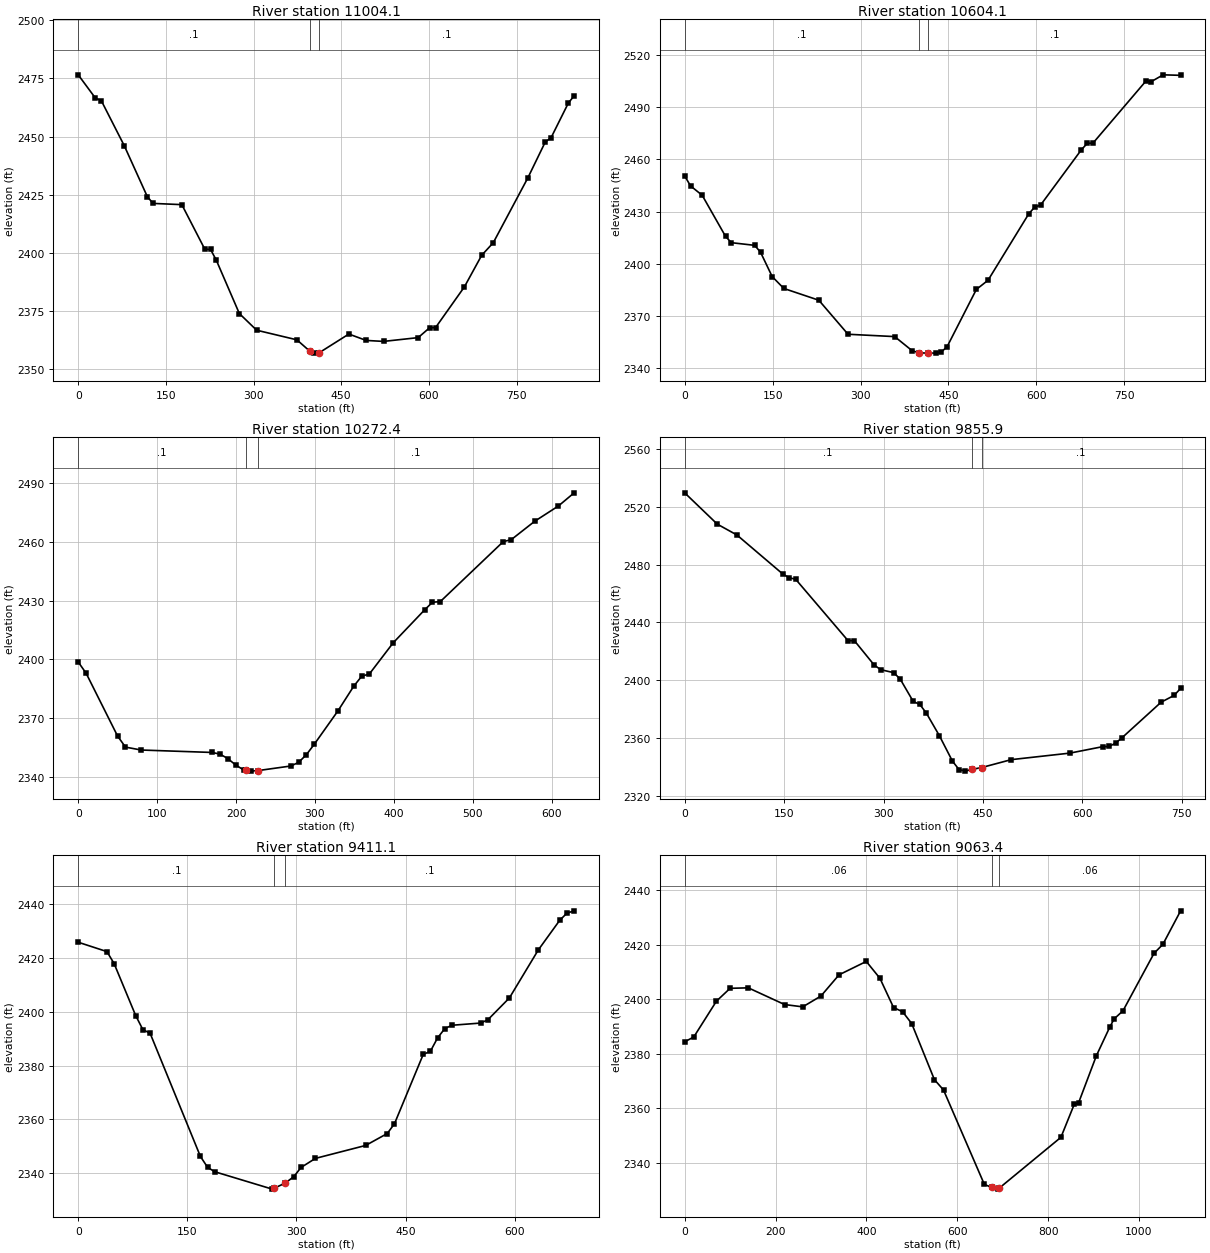
Type RM Length L Ch R = 1 ,11004.1 ,392.7,400,408.5
XS GIS Cut Line= 3
     1914824.975        222992.3     1914839.338      223395.796
     1914936.696      223829.869
#Sta/Elev= 30
       0 2476.55    29.5 2466.51    39.4 2465.49    78.8 2446.07   118.2 2424.19
     128 2421.25   177.3 2420.72   216.6 2401.56   226.5 2401.43   236.3 2396.82
   275.7 2373.89   305.3 2366.72   374.2 2362.58   396.3 2357.69   403.8 2356.86
   411.3 2356.86   463.1 2365.07   492.7 2362.32   522.4  2361.9   581.7 2363.53
   601.5 2367.82   611.4 2367.82   660.8 2385.36   690.4 2398.94   710.2 2404.34
   769.5  2432.3   799.2 2447.68   809.1  2449.5   838.7 2464.43   848.6 2467.53
#Mann= 3 , 0 , 0
       0      .1       0   396.3    .045       0   411.3      .1       0
Bank Sta=396.3,411.3
XS Rating Curve= 0 ,0
Exp/Cntr=0.3,0.1

Type RM Length L Ch R = 1 ,10604.1 ,342.6,331.7,323.8
XS GIS Cut Line= 3
      1914619.88      223004.613     1914503.648      223395.744
     1914431.905      223828.019
#Sta/Elev= 30
       0 2450.47      10 2444.75    29.9 2439.35    69.7 2415.78    79.6 2412.15
   119.4 2410.62   129.4 2406.69   149.3 2392.68   169.2 2385.86   228.9 2379.11
   278.7 2359.57   358.3 2358.23   388.1 2350.13   400.5 2348.91   415.5 2348.79
     428 2348.74   437.9 2349.35   447.9 2352.52   497.7 2385.31   517.6 2390.57
   587.3 2428.82   597.2 2432.55   607.2 2433.71   676.9  2465.5   686.9 2469.17
   696.8 2469.35   786.5 2504.75   796.4 2504.67   816.4 2508.51   846.2 2508.22
#Mann= 3 , 0 , 0
       0      .1       0   400.5    .045       0   415.5      .1       0
Bank Sta=400.5,415.5
XS Rating Curve= 0 ,0
Exp/Cntr=0.3,0.1

Type RM Length L Ch R = 1 ,10272.4 ,415.9,416.5,417
XS GIS Cut Line= 2
     1914145.306      223228.038     1914255.273      223846.859
#Sta/Elev= 30
       0 2398.72      10 2393.01    49.9 2360.96    59.9 2355.33    79.8 2353.85
   169.6 2352.61   179.6 2351.78   189.6 2349.49   199.5 2346.22   209.5 2343.74
   212.8 2343.53   219.5 2343.09   227.8 2343.36   269.4  2345.7   279.3 2347.55
   289.3 2351.54   299.3 2356.87   329.2 2373.83   349.2  2386.4   359.2 2391.43
   369.1 2392.67   399.1 2408.47     439 2425.29   448.9 2429.17   458.9 2429.52
   538.7  2460.1   548.7 2461.06   578.6 2470.49   608.6 2478.27   628.5 2484.96
#Mann= 3 , 0 , 0
       0      .1       0   212.8    .045       0   227.8      .1       0
Bank Sta=212.8,227.8
XS Rating Curve= 0 ,0
Exp/Cntr=0.3,0.1

Type RM Length L Ch R = 1 ,9855.9  ,445.9,444.8,443.7
XS GIS Cut Line= 3
     1913774.177      222946.564     1913865.917      223530.362
     1913895.107      223684.651
#Sta/Elev= 30
       0 2529.64    49.2 2507.98    78.8 2500.49   147.7 2473.61   157.6 2470.94
   167.4 2469.88   246.2 2427.53   256.1 2427.34   285.6 2410.71   295.5 2407.39
   315.2 2405.32     325 2400.92   344.7 2385.41   354.6 2383.36   364.4 2377.42
   384.1 2361.77   403.8 2344.18   413.7 2338.35   423.5 2337.23   432.9  2338.4
   447.9 2339.71   492.5 2345.17   581.1 2349.69   630.2 2354.12     640 2354.26
   649.8 2356.55   659.7 2360.34   718.6 2384.89   738.2 2389.59     748 2394.42
#Mann= 3 , 0 , 0
       0      .1       0   432.9    .045       0   447.9      .1       0
Bank Sta=432.9,447.9
XS Rating Curve= 0 ,0
Exp/Cntr=0.3,0.1

Type RM Length L Ch R = 1 ,9411.1  ,348,347.5,346.6
XS GIS Cut Line= 2
     1913378.029      223284.333     1913516.806      223951.842
#Sta/Elev= 30
       0  2425.9    39.5 2422.41    49.4 2417.92      79 2398.62    88.9 2393.36
    98.8 2392.04     168 2346.17   177.9 2342.11   187.7 2340.48   266.8 2334.01
   269.6 2334.38   284.6 2336.25   296.4 2338.66   306.3 2342.07   326.1 2345.45
   395.2 2350.27   424.9 2354.71   434.8 2358.36   474.3 2384.14   484.2 2385.33
     494 2390.27   503.9 2393.74   513.8    2395   553.3 2395.82   563.2 2397.05
   592.8 2405.18   632.4 2422.99     662 2434.08   671.9 2436.73   681.8 2437.59
#Mann= 3 , 0 , 0
       0      .1       0   269.6    .045       0   284.6      .1       0
Bank Sta=269.6,284.6
XS Rating Curve= 0 ,0
Exp/Cntr=0.3,0.1

Type RM Length L Ch R = 1 ,9063.4  ,340.9,339,336.7
XS GIS Cut Line= 3
     1912946.436      222921.544     1913142.425      223665.886
      1913213.81      223980.004
#Sta/Elev= 30
       0 2384.36      20 2386.12      70 2399.29     100 2403.98     140 2404.16
   219.9 2398.03   259.9 2397.18   299.9 2401.14   339.9 2408.94   399.8 2413.84
   429.8 2407.67   459.8 2396.94   479.8 2395.38   499.8 2391.05   549.8 2370.47
   569.8 2366.69   659.8 2332.01   676.6 2330.93   689.7 2330.31   691.6 2330.55
   828.3 2349.32   857.6 2361.42   867.3 2362.03   906.4 2379.27   935.7 2389.71
   945.4 2392.76   964.9 2395.73  1033.3 2416.83  1052.8 2420.13  1091.8 2432.41
#Mann= 3 , 0 , 0
       0     .06       0   676.6    .045       0   691.6     .06       0
Bank Sta=676.6,691.6
XS Rating Curve= 0 ,0
Exp/Cntr=0.3,0.1

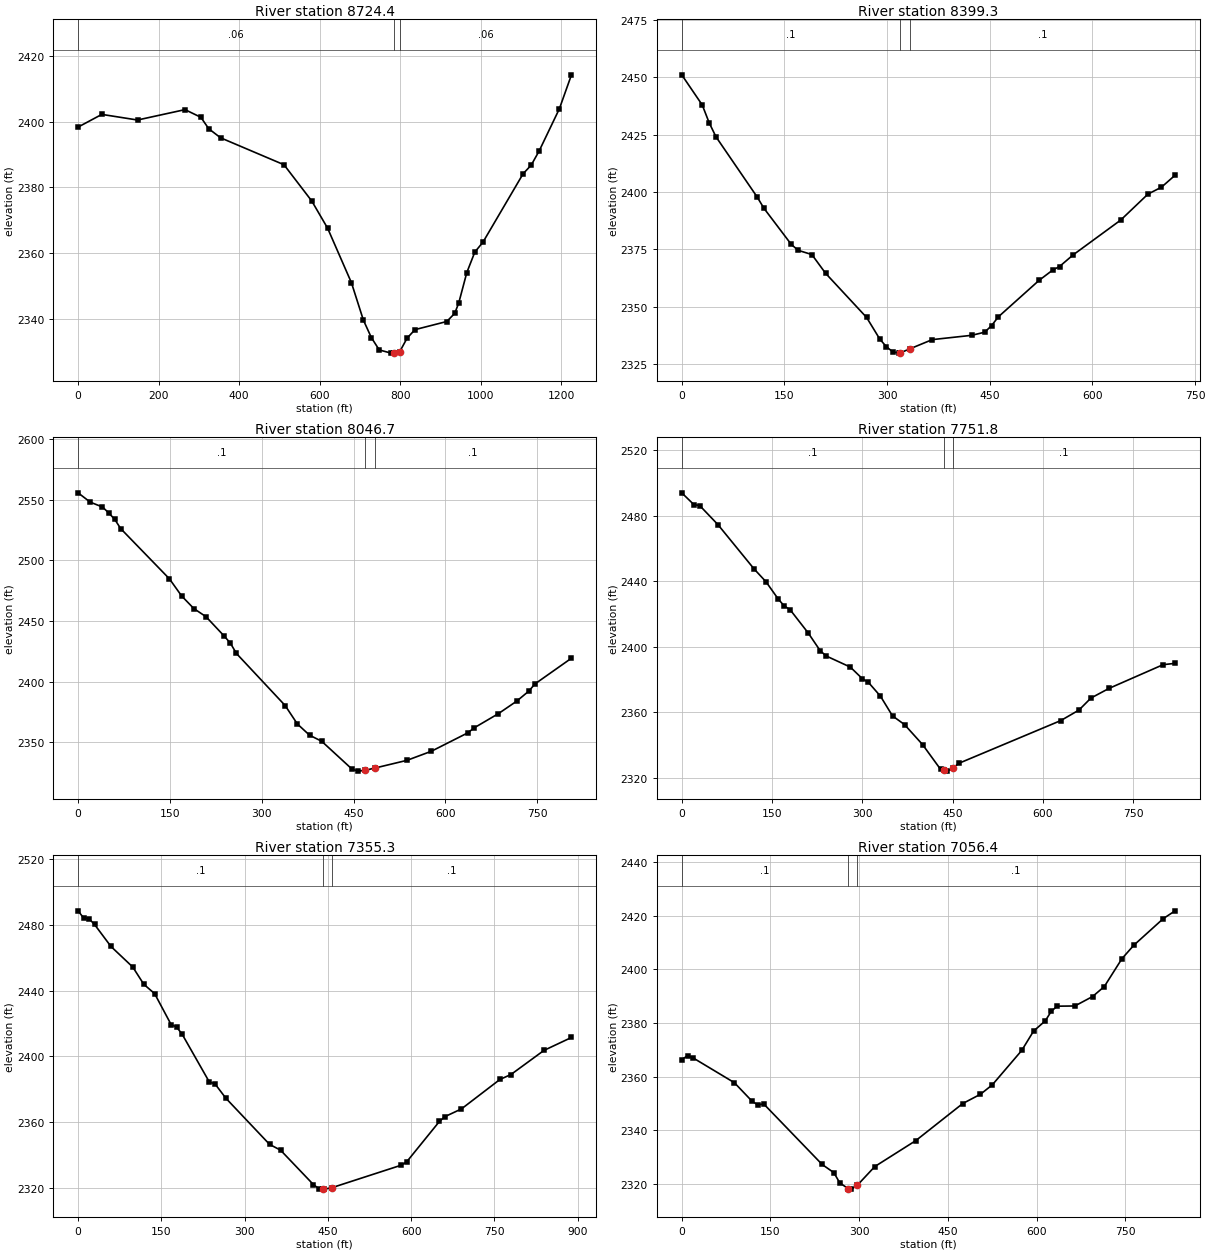
Type RM Length L Ch R = 1 ,8724.4  ,355.1,325.1,295.2
XS GIS Cut Line= 4
     1912569.052      222915.289     1912733.767      223461.557
     1912871.912      223788.675     1913067.365      224016.165
#Sta/Elev= 30
       0 2398.38      59 2402.24   147.6 2400.53   265.6 2403.69     305 2401.36
   324.6 2397.87   354.1 2395.11   511.5 2386.92   580.4  2375.9   619.9  2367.6
   679.1    2351   708.6 2339.68   728.4 2334.35   748.1 2330.57   777.7  2329.6
   783.6 2329.61   798.6 2329.95   817.2 2334.14   836.9 2336.75   915.8 2339.22
   935.6  2341.7   945.6 2344.86   965.6  2354.1   985.6 2360.37  1005.6 2363.33
  1105.6  2384.2  1125.6  2386.8  1145.6 2391.18  1195.6 2403.96  1225.6 2414.28
#Mann= 3 , 0 , 0
       0     .06       0   783.6    .045       0   798.6     .06       0
Bank Sta=783.6,798.6
XS Rating Curve= 0 ,0
Exp/Cntr=0.3,0.1

Type RM Length L Ch R = 1 ,8399.3  ,335.6,352.6,369.3
XS GIS Cut Line= 4
     1912364.723      223861.876     1912633.687      223886.895
     1912804.656      223863.961     1913017.325       224043.27
#Sta/Elev= 30
       0 2451.06      30  2437.9      40 2430.21      50 2424.05     110 2397.88
   120.1 2392.87   160.1  2377.1   170.1 2374.54   190.1  2372.7   210.1 2364.55
   270.1 2345.27   289.3 2335.87   298.9 2332.53   308.5 2330.24     318 2329.72
   318.8  2329.8   333.8 2331.65     366 2335.61   423.5 2337.48   442.6 2338.84
   452.6  2341.7   462.5 2345.52   522.1 2361.46     542 2365.94   551.9 2367.48
   571.8 2372.55   641.3 2387.73   681.1 2399.05   700.9 2402.08   720.8 2407.29
#Mann= 3 , 0 , 0
       0      .1       0   318.8    .045       0   333.8      .1       0
Bank Sta=318.8,333.8
XS Rating Curve= 0 ,0
Exp/Cntr=0.3,0.1

Type RM Length L Ch R = 1 ,8046.7  ,290.6,295,299.3
XS GIS Cut Line= 2
     1912108.269       223909.83     1912790.061      224339.339
#Sta/Elev= 30
       0 2555.74    19.9 2548.05    39.8 2544.06    49.7 2539.37    59.7 2533.98
    69.6 2526.25   149.2 2484.84   169.1 2470.76     189 2460.38   208.9 2453.66
   238.8  2437.6   248.7 2431.88   258.6 2423.36   338.2 2380.43   358.1 2365.26
     378 2356.01   397.9 2350.98   447.7 2327.89   457.6 2326.38   469.4 2327.14
   484.4 2328.87   537.2 2335.28     577 2342.76   636.7 2357.98   646.6 2361.96
   686.4 2373.73   716.3 2384.03   736.2 2392.34   746.1 2398.22   805.8 2419.45
#Mann= 3 , 0 , 0
       0      .1       0   469.4    .045       0   484.4      .1       0
Bank Sta=469.4,484.4
XS Rating Curve= 0 ,0
Exp/Cntr=0.3,0.1

Type RM Length L Ch R = 1 ,7751.8  ,389,396.5,404
XS GIS Cut Line= 3
     1912002.872      224088.543     1912303.393      224367.398
     1912605.134      224644.023
#Sta/Elev= 30
       0    2494      20 2486.86      30 2486.16      60 2474.63     120 2447.58
     140 2439.66     160 2429.27     170 2424.97     180 2422.61     210 2408.43
     230 2397.56     240 2394.36     280 2387.58     300 2380.48     310 2378.25
     330 2369.83     350 2357.79     370 2352.47     400 2340.24   429.9 2325.11
   435.3 2324.54   439.9 2324.06   450.3 2325.87   459.9 2328.79   629.6 2354.96
   659.6 2361.34   679.5 2368.68   709.5 2374.57   799.4 2389.07   819.3 2389.87
#Mann= 3 , 0 , 0
       0      .1       0   435.3    .045       0   450.3      .1       0
Bank Sta=435.3,450.3
XS Rating Curve= 0 ,0
Exp/Cntr=0.3,0.1

Type RM Length L Ch R = 1 ,7355.3  ,303.8,298.5,293.2
XS GIS Cut Line= 3
     1911772.585      224180.879     1912031.124      224668.767
     1912170.819      224975.261
#Sta/Elev= 30
       0  2488.7     9.9 2484.36    19.7 2483.87    29.6  2480.4    59.2 2466.99
    98.6  2454.4   118.3 2443.96     138 2438.18   167.6 2419.38   177.5 2417.84
   187.3  2413.6   236.6 2384.28   246.5  2383.3   266.2 2374.49   345.1  2346.3
   364.8  2342.8     424 2321.82   433.8 2319.34     442 2319.09   443.7 2319.04
     457 2319.88   581.9 2333.59   591.8 2335.56   651.2 2360.36   661.1 2363.25
   690.8 2367.95   760.2 2385.92     780 2388.91   839.4  2403.6     889 2411.49
#Mann= 3 , 0 , 0
       0      .1       0     442    .045       0     457      .1       0
Bank Sta=442,457
XS Rating Curve= 0 ,0
Exp/Cntr=0.3,0.1

Type RM Length L Ch R = 1 ,7056.4  ,431.1,420.9,410.7
XS GIS Cut Line= 3
     1911599.198      224576.372     1911878.699      224897.024
     1912070.748      225257.903
#Sta/Elev= 30
       0 2366.37     9.9 2367.83    19.8 2366.92      89 2357.76   118.7  2350.9
   128.6 2349.47   138.5 2349.87   237.4 2327.27   257.2 2324.23   267.1 2320.45
   281.8 2318.19   286.9 2318.08   296.8 2319.51   326.4 2326.49   395.7 2336.16
   475.2    2350   505.1 2353.45   525.1 2356.95   574.9 2369.79   594.9    2377
   614.8 2380.84   624.8 2384.38   634.8 2386.28   664.7 2386.36   694.6 2389.87
   714.5  2393.6   744.4 2404.02   764.4 2409.01   814.2 2418.93   834.2 2421.83
#Mann= 3 , 0 , 0
       0      .1       0   281.8    .045       0   296.8      .1       0
Bank Sta=281.8,296.8
XS Rating Curve= 0 ,0
Exp/Cntr=0.3,0.1

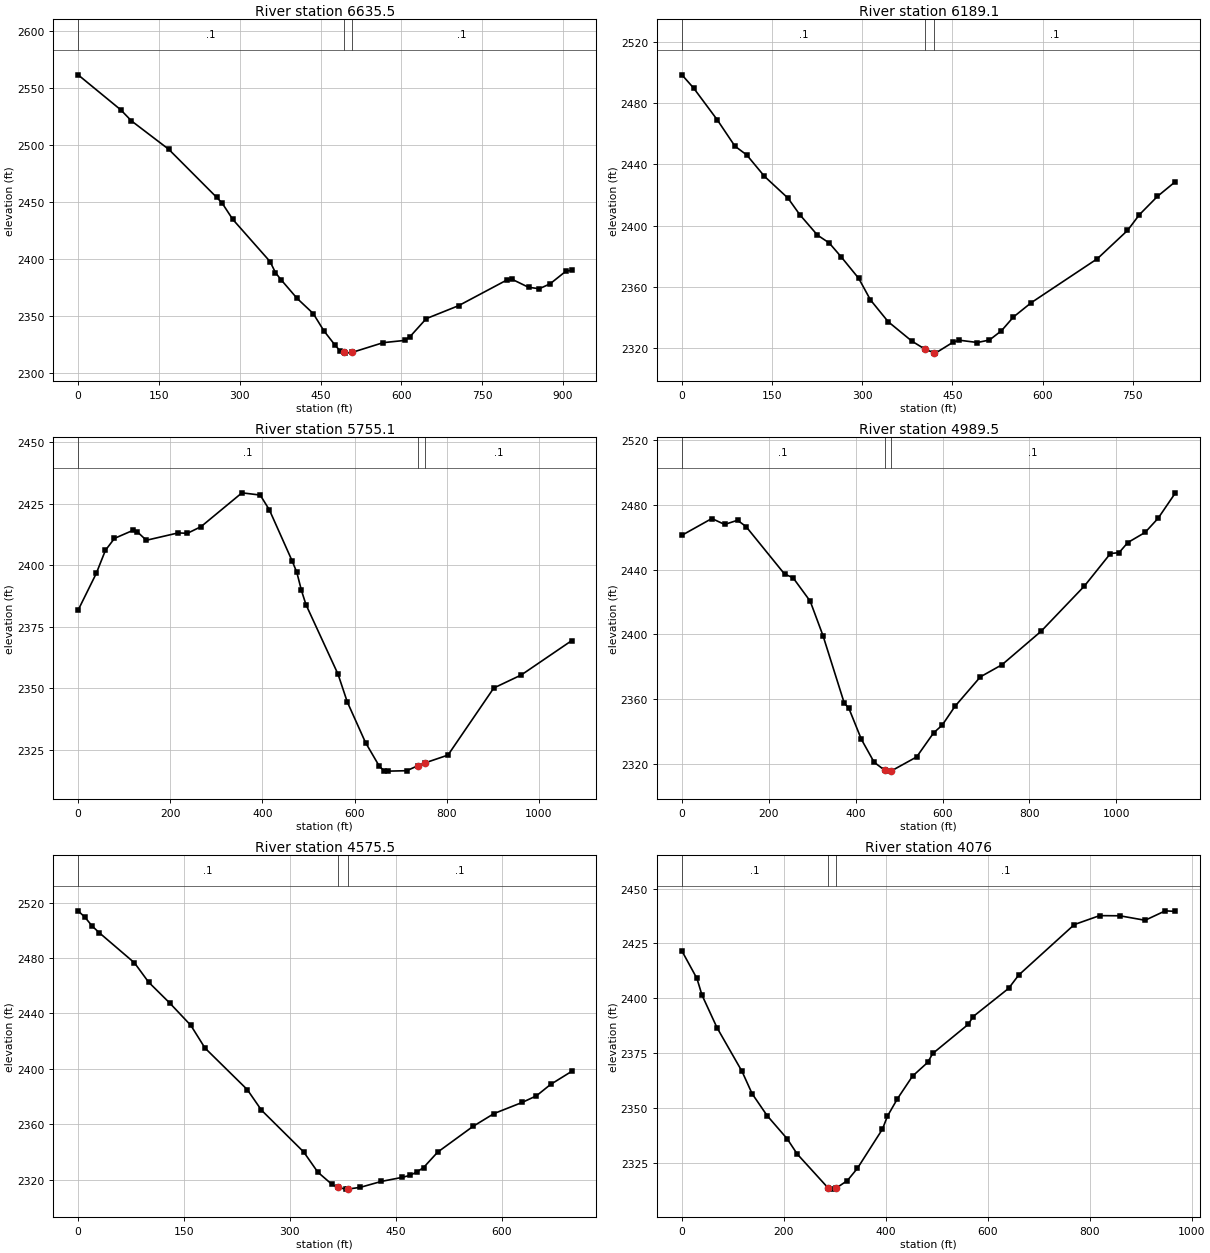
Type RM Length L Ch R = 1 ,6635.5  ,437.2,446.4,453
XS GIS Cut Line= 3
     1911040.753      224877.266     1911357.672      225016.961
      1911878.92       225246.31
#Sta/Elev= 30
       0 2561.72    79.2 2530.99      99 2521.29   168.2 2496.36   257.3  2454.1
   267.2  2449.2     287 2434.87   356.3 2397.76   366.3 2388.05   376.3 2382.07
   406.3 2365.55   436.3 2352.22   456.2 2336.99   476.2 2324.84   486.2 2319.38
   493.2 2318.04   496.2 2317.47   508.2 2318.06   566.1 2326.66   606.1 2328.62
   616.1 2332.04   646.1 2347.74     706  2359.1   795.9 2381.72   805.9 2382.13
   835.9 2375.25   855.9    2374   875.8 2378.28   905.8  2389.6   915.8 2390.05
#Mann= 3 , 0 , 0
       0      .1       0   493.2    .045       0   508.2      .1       0
Bank Sta=493.2,508.2
XS Rating Curve= 0 ,0
Exp/Cntr=0.3,0.1

Type RM Length L Ch R = 1 ,6189.1  ,452.2,433.6,417.6
XS GIS Cut Line= 3
     1911004.495      225154.497     1911284.445      225456.467
     1911596.161      225721.614
#Sta/Elev= 30
       0 2498.48    19.6 2489.78    58.8 2469.07    88.2 2451.87   107.8 2446.15
   137.3 2432.17   176.5  2417.9   196.1  2407.1   225.5 2393.75   245.1 2388.61
   264.7 2379.66   294.1 2365.51   313.7 2351.39   343.1 2337.19   382.4 2324.53
   404.3 2319.24   419.3 2316.92   421.8 2316.65   451.7 2323.94   461.7 2325.08
   491.6 2323.59   511.6 2325.22   531.6 2331.28   551.5 2340.25   581.4 2349.68
   691.2 2378.36   741.2 2396.78   761.1 2407.13   791.1 2419.07     821 2428.72
#Mann= 3 , 0 , 0
       0      .1       0   404.3    .045       0   419.3      .1       0
Bank Sta=404.3,419.3
XS Rating Curve= 0 ,0
Exp/Cntr=0.3,0.1

Type RM Length L Ch R = 1 ,5755.1  ,736.6,765.5,792.7
XS GIS Cut Line= 3
     1910365.398      225629.154      1910713.59      225794.212
     1911399.554      225798.038
#Sta/Elev= 30
       0 2381.74    39.5 2396.72    59.3 2406.09      79 2410.96   118.6 2414.18
   128.4 2413.64   148.2 2410.19   217.4 2413.19   237.1 2413.01   266.8 2415.72
   355.7 2429.49   395.3 2428.58   415.2 2422.56   464.9 2401.67   474.8 2397.13
   484.8  2389.8   494.7 2383.98   564.3 2355.68   584.2 2344.48   623.9  2327.9
   653.8 2318.29   663.7 2316.47   673.6 2316.27   713.4 2316.44   738.5 2318.55
   753.5 2319.65   802.9 2322.79   902.3 2350.08     962 2355.39  1071.3 2369.34
#Mann= 3 , 0 , 0
       0      .1       0   738.5    .045       0   753.5      .1       0
Bank Sta=738.5,753.5
XS Rating Curve= 0 ,0
Exp/Cntr=0.3,0.1

Type RM Length L Ch R = 1 ,4989.5  ,440.5,413.9,388.1
XS GIS Cut Line= 4
     1910507.509      225823.124     1910791.522        226051.1
     1910919.352      226347.665     1911345.452       226489.13
#Sta/Elev= 30
       0  2461.3    68.9 2471.64    98.4 2467.98     128 2470.57   147.6 2466.68
   236.2 2437.36   255.9 2435.04   295.3 2420.59   324.8 2399.28     374 2357.38
   383.8 2354.76   413.1 2335.25   442.5 2321.08   466.4 2316.21   471.8 2315.59
   481.4 2315.62   540.3 2324.35   579.5 2339.26   599.1 2343.95   628.4 2355.55
   687.1 2373.83     737 2381.35   826.8 2401.98   926.6 2429.96   986.4    2450
  1006.4 2450.59  1026.4 2456.79  1066.3 2463.07  1096.2 2471.79  1136.1 2487.52
#Mann= 3 , 0 , 0
       0      .1       0   466.4    .045       0   481.4      .1       0
Bank Sta=466.4,481.4
XS Rating Curve= 0 ,0
Exp/Cntr=0.3,0.1

Type RM Length L Ch R = 1 ,4575.5  ,510.4,499.4,488.5
XS GIS Cut Line= 2
     1910251.811      226480.602     1910951.099      226472.285
#Sta/Elev= 30
       0 2514.01      10 2509.21      20 2502.97      30 2498.21    79.9 2476.47
    99.9 2462.57   129.9 2447.47   159.8 2431.35   179.8 2415.03   239.8    2385
   259.8 2370.23   319.7 2340.04   339.7 2325.49   359.7 2316.69     368 2314.49
   379.6 2313.26     383 2313.37   399.6 2314.51   429.6 2318.81   459.6 2321.78
   469.6  2323.1   479.6 2325.47   489.5 2328.82   509.5 2339.95   559.5 2358.49
   589.4 2367.78   629.4 2375.83   649.4 2380.56   669.4 2388.74   699.3 2398.18
#Mann= 3 , 0 , 0
       0      .1       0     368    .045       0     383      .1       0
Bank Sta=368,383
XS Rating Curve= 0 ,0
Exp/Cntr=0.3,0.1

Type RM Length L Ch R = 1 ,4076    ,497.4,522.8,548.2
XS GIS Cut Line= 3
     1910569.545      227066.507     1910967.062      226850.435
     1911482.772      226853.838
#Sta/Elev= 30
       0 2421.57    29.5 2409.01    39.3  2401.5    68.8 2386.61     118 2366.62
   137.7  2356.5   167.2 2346.48   206.6  2335.9   226.2 2328.98   286.6 2313.56
   295.1 2312.98   301.6 2313.27   324.6 2316.88   344.2 2322.43   393.4 2340.33
   403.3 2346.28   422.9 2354.22   452.4 2364.49   482.2 2370.77   492.1 2374.83
   561.5 2388.06   571.5 2391.68   640.9  2404.5   660.7 2410.57   769.8 2433.59
   819.4 2437.67   859.1  2437.6   908.7 2435.55   948.3 2439.86   968.2 2439.59
#Mann= 3 , 0 , 0
       0      .1       0   286.6    .045       0   301.6      .1       0
Bank Sta=286.6,301.6
XS Rating Curve= 0 ,0
Exp/Cntr=0.3,0.1

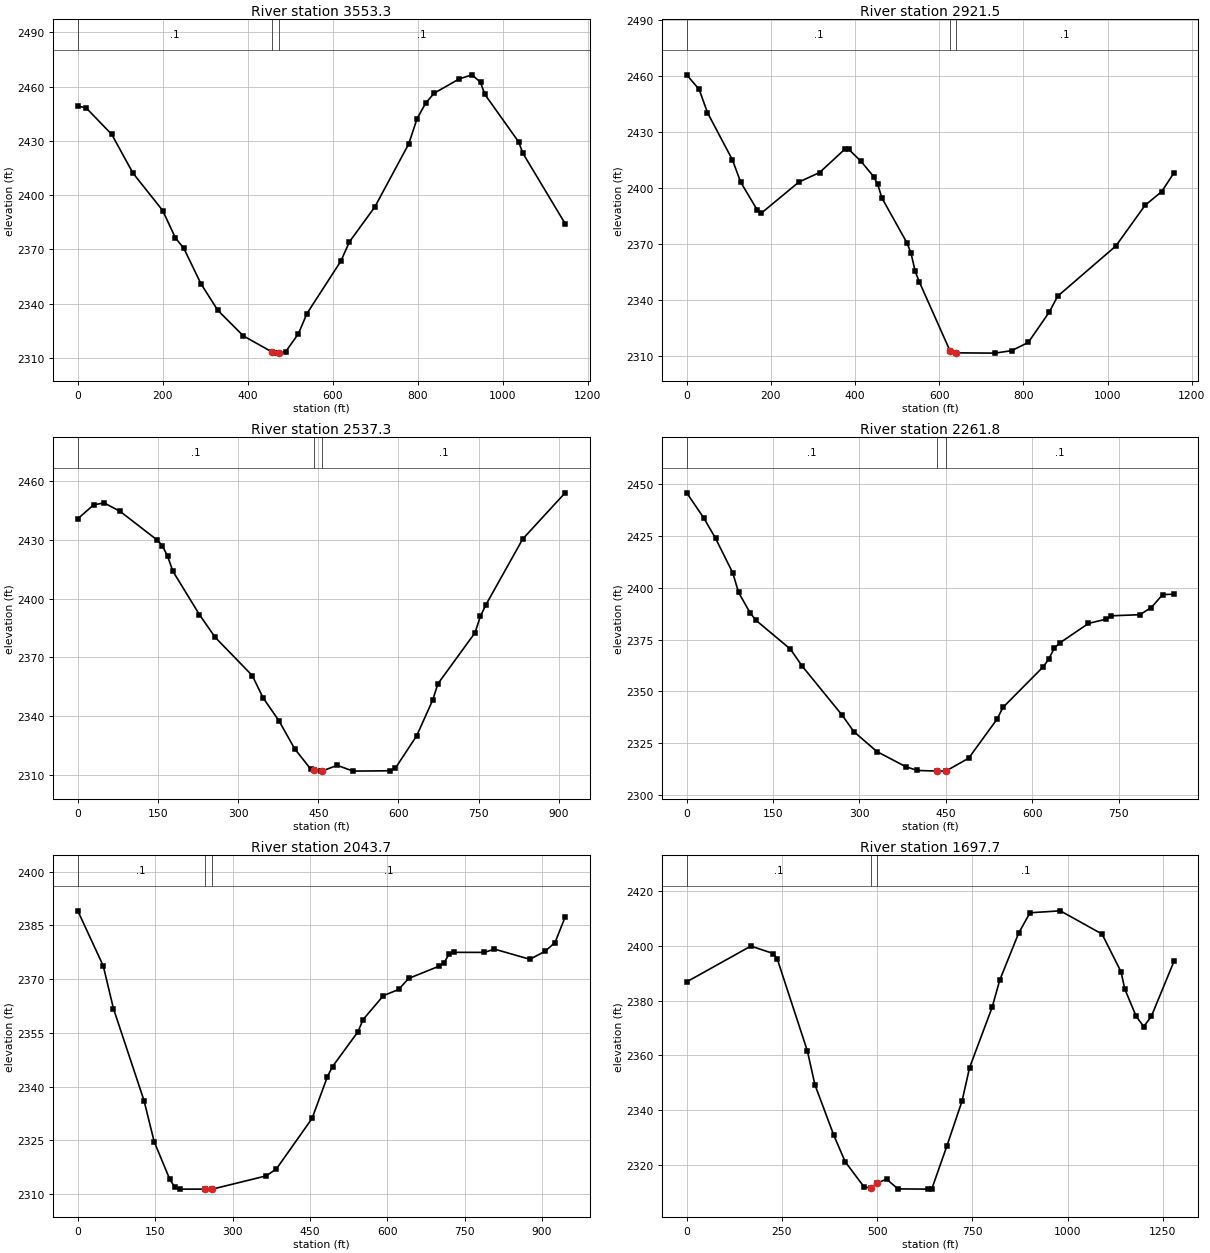
Type RM Length L Ch R = 1 ,3553.3  ,647,631.5,614.7
XS GIS Cut Line= 3
     1910499.128      227149.684     1911019.221      227521.258
     1911526.118      227549.266
#Sta/Elev= 30
       0 2449.31      20 2448.17    79.9 2433.56   129.8  2412.2   199.8 2391.51
   229.7  2376.4   249.7 2370.54   289.6 2351.13   329.6 2336.33   389.5 2322.25
     458 2313.21   469.4  2312.7     473 2312.72   489.4 2313.57   519.3 2323.48
   539.3 2334.59   619.2  2363.6   639.2 2374.19   698.9 2393.45   778.6 2428.23
   798.5 2442.31   818.4 2450.73   838.3  2456.3     898 2464.29   927.9  2466.5
   947.8 2462.34   957.7 2455.77  1037.4 2429.46  1047.3 2423.22  1146.9 2384.24
#Mann= 3 , 0 , 0
       0      .1       0     458    .045       0     473      .1       0
Bank Sta=458,473
XS Rating Curve= 0 ,0
Exp/Cntr=0.3,0.1

Type RM Length L Ch R = 1 ,2921.5  ,406.4,384.2,392.6
XS GIS Cut Line= 4
     1910004.513      227696.175     1910515.741      227806.592
     1910915.654      227725.365     1911137.248      227774.781
#Sta/Elev= 30
       0  2460.7    29.6 2452.87    49.3 2440.46   108.6  2415.2   128.3 2403.24
   167.8 2388.28   177.6 2386.73   266.4 2403.29   315.8 2408.42     375 2420.75
   384.9 2420.85   414.5 2414.33   444.1 2406.24   453.9 2402.01   463.8  2394.8
     523 2370.92     533 2365.29   542.9 2355.49   552.9 2349.77   625.6 2313.02
   640.6  2311.9     732 2311.75   771.8 2313.05   811.7 2317.47   861.4 2333.68
   881.3 2342.18  1019.9 2369.13    1089 2390.83  1128.5 2398.19  1158.1 2408.32
#Mann= 3 , 0 , 0
       0      .1       0   625.6    .045       0   640.6      .1       0
Bank Sta=625.6,640.6
XS Rating Curve= 0 ,0
Exp/Cntr=0.3,0.1

Type RM Length L Ch R = 1 ,2537.3  ,268.5,275.5,281.9
XS GIS Cut Line= 3
     1910290.156      227900.504       1910534.1      227981.819
     1911182.533      228073.558
#Sta/Elev= 30
       0 2440.77    29.7 2447.91    49.4 2448.86    79.1 2444.58   148.4 2429.95
   158.2 2427.06   168.1 2421.59     178 2413.95   227.5 2391.84   257.1 2380.18
   326.6 2360.61   346.4  2349.4   376.2 2337.64     406 2323.14   435.8 2312.87
   441.9 2312.25   455.6 2311.79   456.9 2311.81   485.4 2314.75   515.1  2311.8
   584.6 2311.97   594.5 2313.36   634.2 2329.88     664 2348.02   673.9 2356.44
   743.4 2382.55   753.3 2390.86   763.2 2396.56   832.6 2430.44     912 2454.04
#Mann= 3 , 0 , 0
       0      .1       0   441.9    .045       0   456.9      .1       0
Bank Sta=441.9,456.9
XS Rating Curve= 0 ,0
Exp/Cntr=0.3,0.1

Type RM Length L Ch R = 1 ,2261.8  ,229.4,218.1,207.4
XS GIS Cut Line= 3
     1910294.629      228080.848     1910677.585       228276.68
     1911057.286      228446.855
#Sta/Elev= 30
       0 2445.95      30 2433.63      50 2423.98      80 2407.22      90 2397.82
     110 2387.95     120 2384.37     180 2370.38   200.1 2362.29   270.1 2338.35
   290.1  2330.5   330.1 2320.86   380.1 2313.56   400.1 2311.71   434.8  2311.4
   449.8 2311.38   489.6 2317.65   539.1 2336.63     549 2342.18   618.4 2361.65
   628.3 2365.36   638.2 2370.89   648.1 2373.43   697.6 2382.81   727.3  2384.8
   737.2 2386.48   786.8 2387.02   806.6 2390.48   826.4 2396.73   846.2 2396.96
#Mann= 3 , 0 , 0
       0      .1       0   434.8    .045       0   449.8      .1       0
Bank Sta=434.8,449.8
XS Rating Curve= 0 ,0
Exp/Cntr=0.3,0.1

Type RM Length L Ch R = 1 ,2043.7  ,340.3,346,351.2
XS GIS Cut Line= 3
     1910323.516      228463.452     1910915.654      228442.602
     1911253.423      228542.681
#Sta/Elev= 30
       0 2389.07    49.4 2373.69    69.1 2361.81   128.4 2336.11   148.1 2324.64
   177.8 2314.32   187.6    2312   197.5  2311.4   245.8  2311.4   260.8  2311.4
   365.4  2315.1   385.1 2317.06   454.2 2331.14   483.9 2342.78   493.8 2345.61
   543.1 2355.31     553 2358.71   592.5  2365.4   621.9 2367.12   641.4  2370.2
   700.2 2373.61   709.9 2374.53   719.7 2376.96   729.5 2377.48   788.2 2377.47
   807.8 2378.38   876.3 2375.55   905.6 2377.75   925.2 2380.22   944.8 2387.36
#Mann= 3 , 0 , 0
       0      .1       0   245.8    .045       0   260.8      .1       0
Bank Sta=245.8,260.8
XS Rating Curve= 0 ,0
Exp/Cntr=0.3,0.1

Type RM Length L Ch R = 1 ,1697.7  ,228.7,246.3,264
XS GIS Cut Line= 3
     1910147.446      228690.977     1911021.988       228801.22
     1911411.882      228882.535
#Sta/Elev= 30
       0 2386.82   168.4 2399.85   227.8 2397.12   237.7 2395.19   316.9 2361.61
   336.7 2349.31   386.3 2330.91     416  2321.3   465.5 2312.13   483.8 2311.69
   498.8 2313.44   524.9 2314.93   554.6 2311.37   633.9 2311.29   643.8 2311.46
   683.4  2327.1     723 2343.39   742.8 2355.57   802.2 2377.61     822 2387.45
   871.6 2404.56   901.4 2411.99     981  2412.7  1090.6 2404.24  1140.4 2390.51
  1150.3 2384.25  1180.2 2374.24  1200.1 2370.52    1220 2374.23  1279.8 2394.36
#Mann= 3 , 0 , 0
       0      .1       0   483.8    .045       0   498.8      .1       0
Bank Sta=483.8,498.8
XS Rating Curve= 0 ,0
Exp/Cntr=0.3,0.1

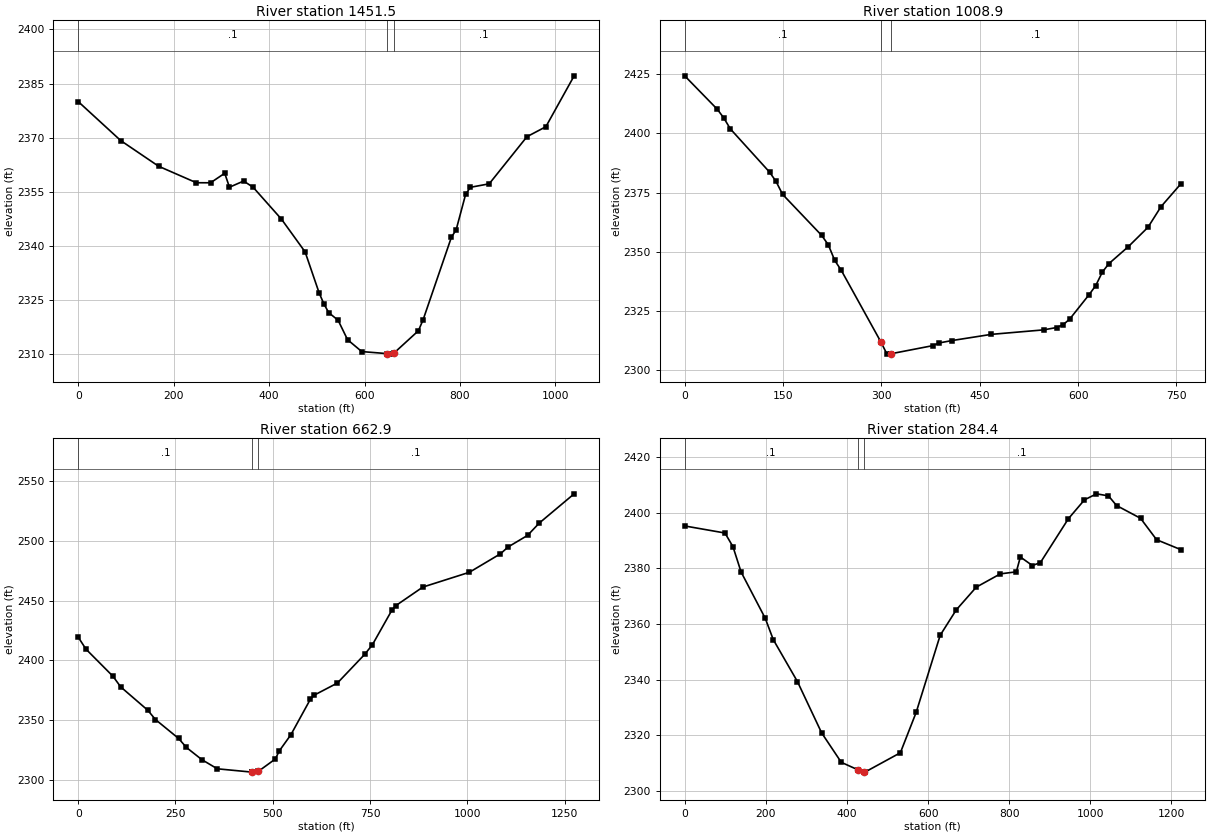
Type RM Length L Ch R = 1 ,1451.5  ,464.8,442.4,420.1
XS GIS Cut Line= 3
     1909972.456      228704.008     1910427.505      228841.617
     1910790.294       229273.21
#Sta/Elev= 30
       0 2379.99    89.1 2369.17   168.4 2362.06   247.6 2357.48   277.3 2357.47
     307 2360.11   316.9 2356.24   346.6 2357.95   366.5 2356.23   425.9 2347.38
   475.4 2338.31   505.1 2326.83     515 2323.83   524.9 2321.46   544.6 2319.34
   564.4 2313.95   594.1 2310.66   647.2 2310.09   653.4 2309.95   662.2 2310.31
   712.8 2316.43   722.7 2319.48     782 2342.37   791.9 2344.41   811.7 2354.22
   821.6 2356.21   861.2 2357.18   940.3 2370.25   979.9 2373.01  1039.2 2387.13
#Mann= 3 , 0 , 0
       0      .1       0   647.2    .045       0   662.2      .1       0
Bank Sta=647.2,662.2
XS Rating Curve= 0 ,0
Exp/Cntr=0.3,0.1

Type RM Length L Ch R = 1 ,1008.9  ,347.7,345.9,343.6
XS GIS Cut Line= 2
     1910009.986      229349.834     1910762.146      229270.083
#Sta/Elev= 30
       0 2424.32    49.8 2410.18    59.7 2406.51    69.7  2401.9   129.4 2383.68
   139.3 2379.75   149.3 2374.27     209 2356.92     219 2352.99   228.9 2346.37
   238.9 2342.16   299.6 2311.78   308.5 2306.81   314.6 2306.97   378.2 2310.38
   388.1 2311.53     408 2312.56   467.8 2315.16   547.4 2317.05   567.3 2318.05
   577.2 2319.23   587.2  2321.6     617 2331.98     627 2335.78     637 2341.44
   646.9 2344.99   676.8 2352.23   706.6 2360.36   726.5 2369.08   756.4 2378.59
#Mann= 3 , 0 , 0
       0      .1       0   299.6    .045       0   314.6      .1       0
Bank Sta=299.6,314.6
XS Rating Curve= 0 ,0
Exp/Cntr=0.3,0.1

Type RM Length L Ch R = 1 ,662.9   ,376.5,378.2,380.3
XS GIS Cut Line= 3
     1910058.429       229684.39     1910507.254       229599.95
     1911306.913      229428.554
#Sta/Elev= 30
       0 2419.43    19.9 2409.44    89.4 2386.74   109.2 2377.91   178.7 2358.43
   198.6 2350.63   258.1 2334.83     278 2327.36   317.7 2317.18   357.4 2309.53
   446.8 2306.75   447.4 2306.75   462.4 2307.29   506.6 2317.71   516.5 2324.36
   546.5 2337.94   596.3  2367.4   606.3 2370.99   666.1 2381.14     736 2404.99
   755.9 2413.03   805.8 2441.78   815.7 2445.64   885.6 2461.24  1005.2 2473.59
    1085 2489.01    1105 2494.78  1154.8  2504.4  1184.8 2514.67  1274.5  2539.1
#Mann= 3 , 0 , 0
       0      .1       0   447.4    .045       0   462.4      .1       0
Bank Sta=447.4,462.4
XS Rating Curve= 0 ,0
Exp/Cntr=0.3,0.1

Type RM Length L Ch R = 1 ,284.4   ,278.2,284.3,288.6
XS GIS Cut Line= 4
     1910030.314      229965.949     1910367.676      229954.631
     1910590.625      229943.203     1911225.102      230131.523
#Sta/Elev= 30
       0 2395.22    99.3 2392.68   119.1 2387.75     139 2378.69   198.6 2362.04
   218.4 2354.37     278 2339.29   337.6 2320.87   386.1 2310.28   426.4 2307.64
   441.4 2306.88   444.3 2306.76   531.7 2313.72   570.7 2328.24   629.9 2355.94
   669.4 2365.04   718.8 2373.22   778.1    2378   817.6 2378.73   827.5 2384.07
   857.1    2381   876.9 2382.04     946 2397.83   985.6  2404.6  1015.2 2406.76
  1044.8 2406.02  1064.6 2402.56  1123.8 2397.97  1163.4 2390.27  1222.6 2386.74
#Mann= 3 , 0 , 0
       0      .1       0   426.4    .045       0   441.4      .1       0
Bank Sta=426.4,441.4
XS Rating Curve= 0 ,0
Exp/Cntr=0.3,0.1

Chan Stop Cuts=-1
Use User Specified Reach Order=0
Composite Channel Slope=5